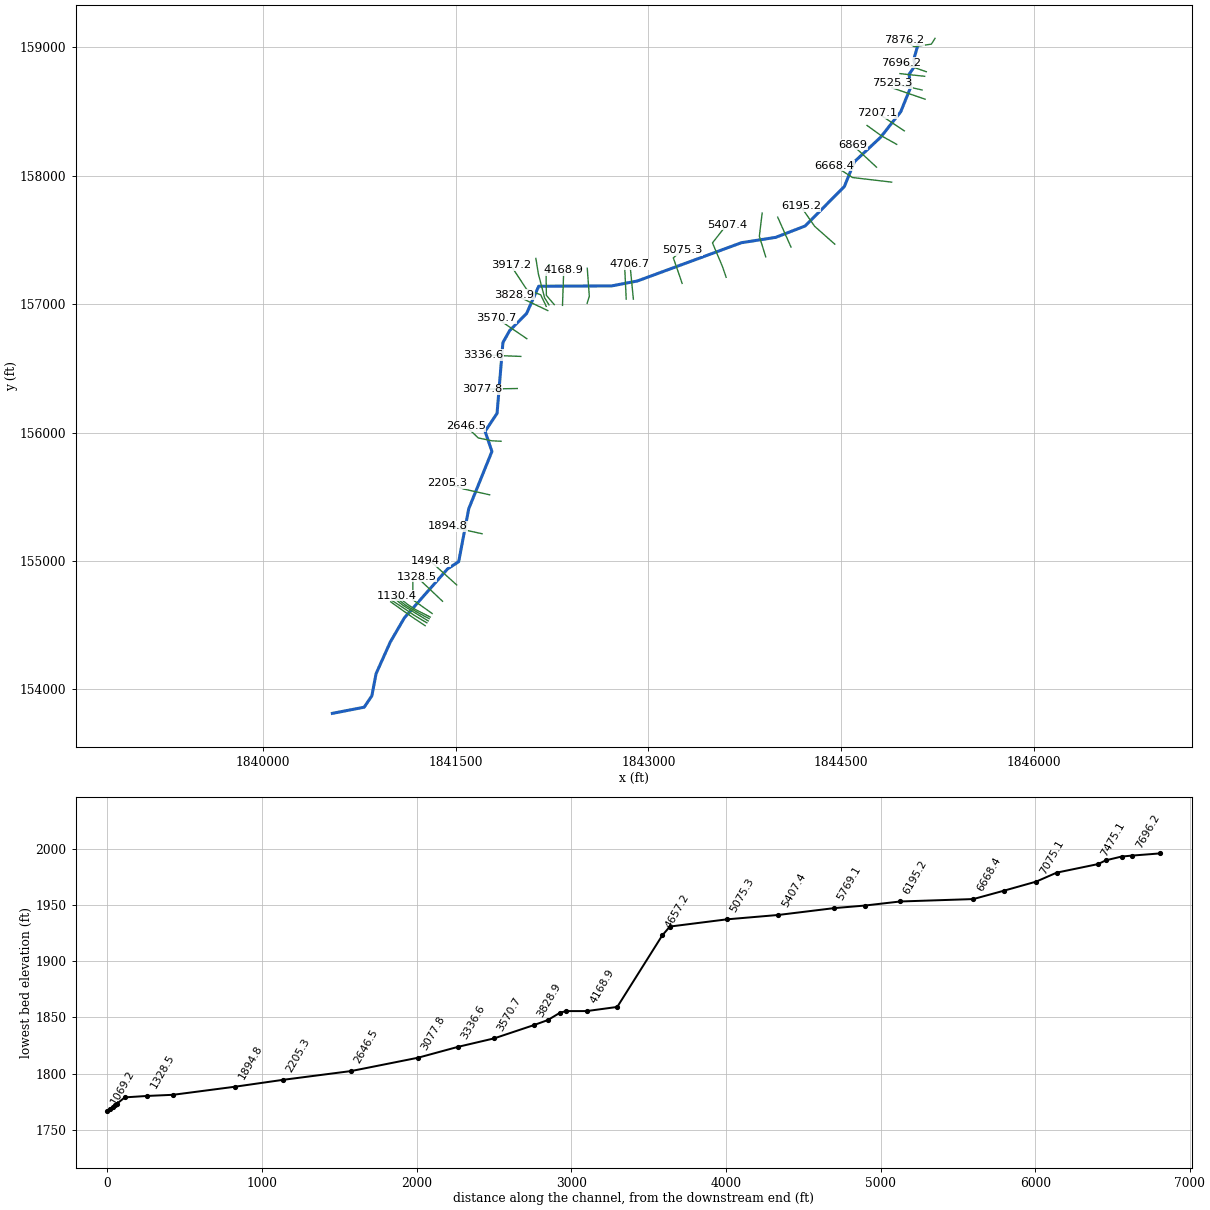
--- Burk Creek.prj (project) ---

Proj Title=Burk Creek
Current Plan=p01
Default Exp/Contr=0,0
English Units
Geom File=g01
Flow File=f01
Plan File=p01
BEGIN DESCRIPTION:
END DESCRIPTION:
DSS Export Rating Curves= 0
DSS Export Rating Curve Sorted= 0
DSS Export Volume Flow Curves= 0
DXF OffsetX= 0
DXF OffsetY= 0
DXF ScaleX= 0
DXF ScaleY= 0

--- Burk Creek.p01 (plan) ---

Plan Title=Floodplain
Program Version=4.00
Geom File=g01
Flow File=f01
K Sum by GR=0
Std Step Tol=0.01
Critical Tol=0.01
Num of Std Step Trials=20
Max Error Tol=0.3
Flow Tol Ratio=0.001
Split Flow NTrial=30
Split Flow Tol=0.02
Split Flow Ratio=0.02
Log Output Level=0
Friction Slope Method=1
Unsteady Friction Slope Method=2
Unsteady Bridges Friction Slope Method=1
Global Log Level=0
CheckData=False
Run HTab=0
Run UNet=0
Run PostProcess=0
UNET Theta=0
UNET Theta Warmup=0
UNET ZTol=0
UNET ZSATol=0
UNET MxIter=0
UNET MaxInSteps=0
UNET DtIC=0
UNET DtMin=0
UNET MaxCRTS=0
UNET WFStab=0
UNET SFStab=0
UNET WFX=0
UNET SFX=0
UNET DSS MLevel=0
UNET DZMax Abort=0
UNET Convert EG Bridges=0
UNET Use Existing IB Tables=0
UNET Froude Limit=0
UNET Froude Power=0
Write IC File=0
Echo Input=False
Echo Output=False
Write Detailed=0

--- Burk Creek.f01 (steady flow) ---

Flow Title=NFF Regression Equation
Program Version=4.00
Number of Profiles=1
Profile Names=P100yr
River Rch & RM=Burk Creek,Main      ,7876.2
561.5336
River Rch & RM=Burk Creek,Main      ,5967.3
623.0557
River Rch & RM=Burk Creek,Main      ,4168.9
659.1126
River Rch & RM=Burk Creek,Main      ,3570.7
935.4767
River Rch & RM=Burk Creek,Main      ,284.1
1026.841
Boundary for River Rch & Prof#=Burk Creek,Main      ,1
Up Type=0
Dn Type=3
Dn Slope=0.063751

--- Burk Creek.g01 (geometry) ---

Geom Title=Geometry
Program Version=4.00

River Reach=Burk Creek      ,Main
Reach XY= 30
      1845098.63       159019.48     1845065.712      158904.624
      1845077.23      158860.345     1845029.747      158790.568
     1845042.864      158692.512     1844965.323      158500.103
     1844808.189      158300.898     1844604.102      158109.894
     1844525.583      157916.668     1844220.485      157609.593
     1843991.114      157520.881      1843724.18      157479.323
     1842914.231      157181.152     1842714.553      157142.857
     1842145.604      157140.232     1842051.084      156927.442
     1841919.581      156795.205     1841866.833      156701.698
     1841821.279      156150.249     1841728.069      156010.016
      1841781.29      155853.357     1841600.553      155406.569
     1841522.377      154994.602     1841435.264      154937.859
     1841099.599      154557.438     1840989.939      154368.975
     1840879.082      154122.309     1840846.252      153950.044
     1840786.549      153861.256     1840538.406      153813.086

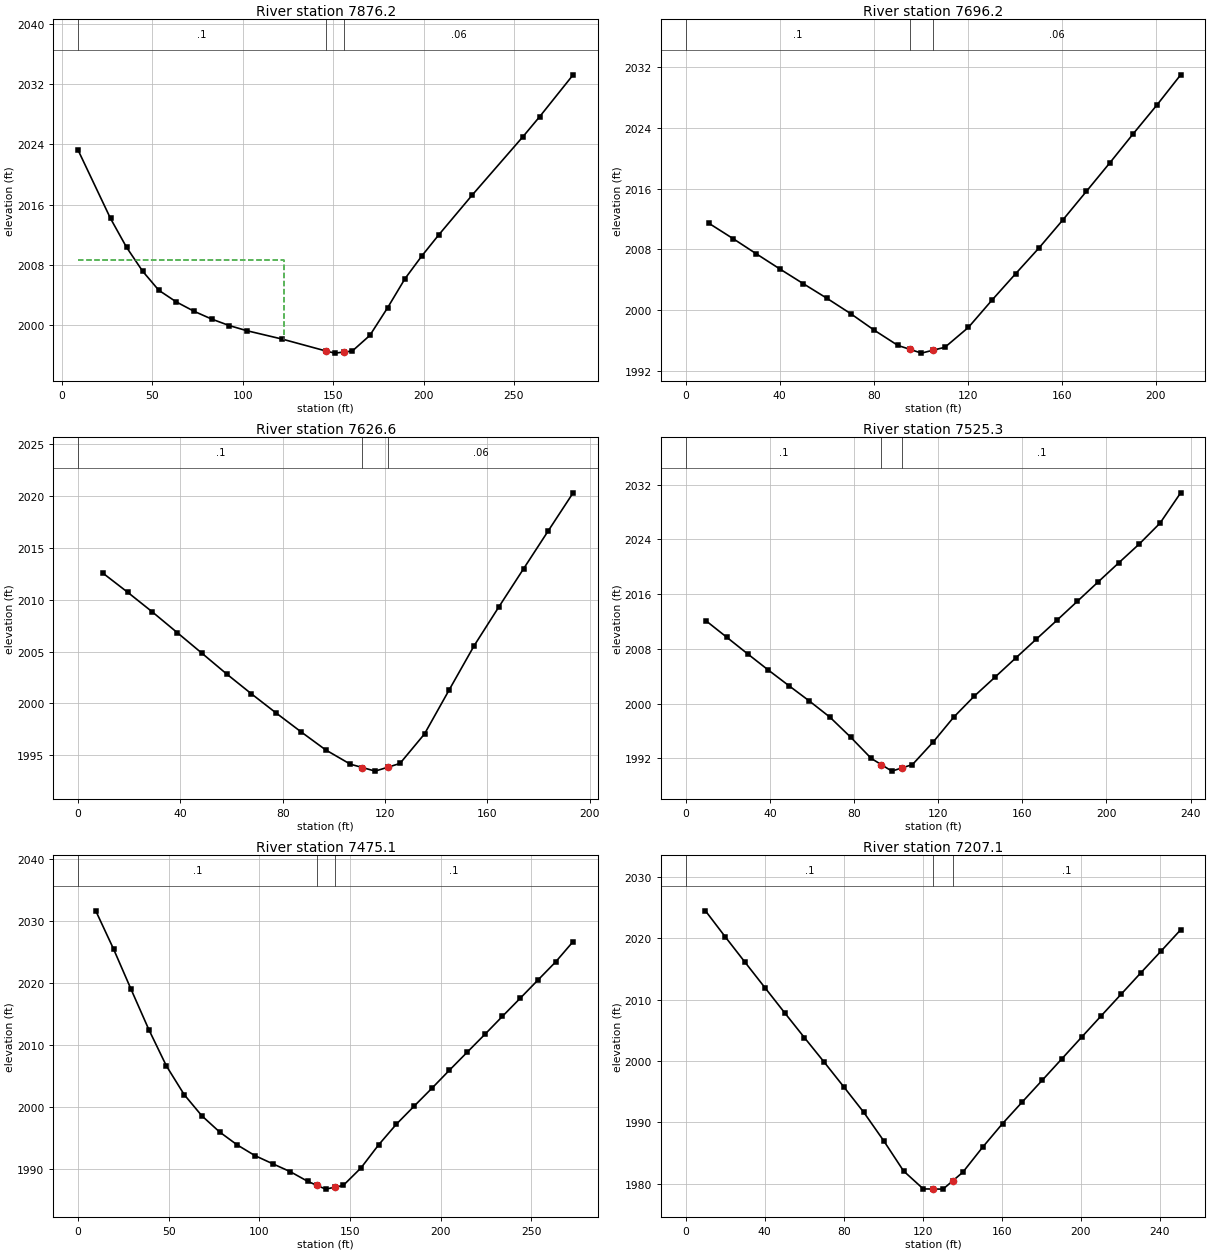
Type RM Length L Ch R = 1 ,7876.2  ,190.1,180,169.8
XS GIS Cut Line= 4
     1845231.903      159071.236     1845203.379       159025.96
     1845068.442      159006.684     1844991.088      159058.306
#Sta/Elev= 24
     8.9 2023.21    26.8 2014.16    35.7 2010.32    44.6 2007.15    53.5 2004.63
    63.2 2003.08      73 2001.84    82.7 2000.81    92.5 1999.94   102.2 1999.26
   121.7 1998.15   145.9 1996.57   150.9 1996.28   155.9 1996.42   160.6 1996.56
   170.3 1998.63   180.1 2002.29   189.8 2006.18   199.1 2009.19   208.4 2011.97
     227 2017.28   254.9 2024.98   264.2 2027.65   282.8 2033.23
#Mann= 3 , 0 , 0
     8.9      .1       0   145.9    .045       0   155.9     .06       0
#XS Ineff= 2 , 0
          122.82 2008.58
Permanent Ineff=
       F       F
Bank Sta=145.9,155.9
XS Rating Curve= 0 ,0
Exp/Cntr=0.3,0.1

Type RM Length L Ch R = 1 ,7696.2  ,64.9,69.6,74.3
XS GIS Cut Line= 2
     1845164.022      158811.026     1844965.228      158880.523
#Sta/Elev= 23
      10  2011.4    20.1 2009.42    30.1  2007.4    40.1 2005.41    50.1 2003.47
    60.2 2001.54    70.2 1999.54    80.2 1997.37    90.3 1995.36    95.3 1994.86
   100.3 1994.35   105.3 1994.74   110.3 1995.12   120.3 1997.74   130.4 2001.35
   140.4  2004.8   150.4 2008.21   160.5 2011.88   170.5 2015.63   180.5 2019.39
   190.5 2023.23   200.6 2027.02   210.6 2030.95
#Mann= 3 , 0 , 0
       0      .1       0    95.3    .045       0   105.3     .06       0
Bank Sta=95.3,105.3
XS Rating Curve= 0 ,0
Exp/Cntr=0.3,0.1

Type RM Length L Ch R = 1 ,7626.6  ,103.7,101.3,98.9
XS GIS Cut Line= 2
     1845151.093      158775.469     1844958.763       158796.48
#Sta/Elev= 22
     9.7 2012.57    19.3 2010.74      29 2008.83    38.7 2006.84    48.4 2004.84
      58 2002.85    67.7 2000.93    77.4 1999.07    87.1 1997.26    96.7 1995.52
   106.4 1994.13   111.1 1993.81   116.1 1993.46   121.1 1993.84   125.8  1994.2
   135.4 1997.05   145.1 2001.33   154.8 2005.57   164.5 2009.33   174.1 2012.99
   183.8 2016.67   193.5 2020.33
#Mann= 3 , 0 , 0
       0      .1       0   111.1    .045       0   121.1     .06       0
Bank Sta=111.1,121.1
XS Rating Curve= 0 ,0
Exp/Cntr=0.3,0.1

Type RM Length L Ch R = 1 ,7525.3  ,52.4,50.2,48
XS GIS Cut Line= 2
     1845131.698      158668.799     1844902.196      158720.518
#Sta/Elev= 26
     9.8 2012.06    19.6 2009.67    29.4 2007.27    39.2 2004.91      49 2002.62
    58.8 2000.36    68.6 1997.99    78.4 1995.08    88.2 1991.97      93 1991.06
      98 1990.11     103  1990.6   107.8 1991.07   117.6 1994.35   127.4    1998
   137.2 2001.08     147 2003.84   156.8 2006.63   166.6 2009.39   176.4 2012.15
   186.2 2014.95     196 2017.76   205.9 2020.58   215.7 2023.35   225.5 2026.38
   235.3 2030.81
#Mann= 3 , 0 , 0
       0      .1       0      93    .045       0     103      .1       0
Bank Sta=93,103
XS Rating Curve= 0 ,0
Exp/Cntr=0.3,0.1

Type RM Length L Ch R = 1 ,7475.1  ,272.7,268,263.2
XS GIS Cut Line= 3
     1845154.482      158597.252     1845025.377      158641.572
     1844896.309      158685.997
#Sta/Elev= 30
     9.7  2031.6    19.5 2025.46    29.2 2018.94      39 2012.45    48.7 2006.59
    58.5 2001.98    68.2 1998.58      78 1995.97    87.7 1993.89    97.5 1992.16
   107.2 1990.86     117 1989.57   126.7    1988   131.5 1987.39   136.5 1986.76
   141.5 1987.07   146.2 1987.35     156 1990.18   165.7 1993.89   175.5 1997.22
   185.2  2000.1     195 2002.98   204.7  2005.9   214.5  2008.8   224.3 2011.69
     234  2014.6   243.8 2017.51   253.5 2020.42   263.3 2023.35     273 2026.65
#Mann= 3 , 0 , 0
       0      .1       0   131.5    .045       0   141.5      .1       0
Bank Sta=131.5,141.5
XS Rating Curve= 0 ,0
Exp/Cntr=0.3,0.1

Type RM Length L Ch R = 1 ,7207.1  ,130.5,132,131.3
XS GIS Cut Line= 2
     1844992.838      158350.278     1844784.346      158489.272
#Sta/Elev= 27
      10 2024.48      20 2020.25    30.1 2016.07    40.1 2011.96    50.1 2007.86
    60.1 2003.81    70.2 1999.78    80.2 1995.72    90.2 1991.61   100.2 1987.02
   110.3 1982.07   120.3 1979.14   125.3 1979.13   130.3 1979.11   135.3 1980.49
   140.3 1981.86   150.3 1985.93   160.4 1989.79   170.4 1993.32   180.4 1996.82
   190.4 2000.34   200.5  2003.9   210.5 2007.41   220.5  2010.9   230.5  2014.4
   240.6 2017.89   250.6 2021.39
#Mann= 3 , 0 , 0
       0      .1       0   125.3    .045       0   135.3      .1       0
Bank Sta=125.3,135.3
XS Rating Curve= 0 ,0
Exp/Cntr=0.3,0.1

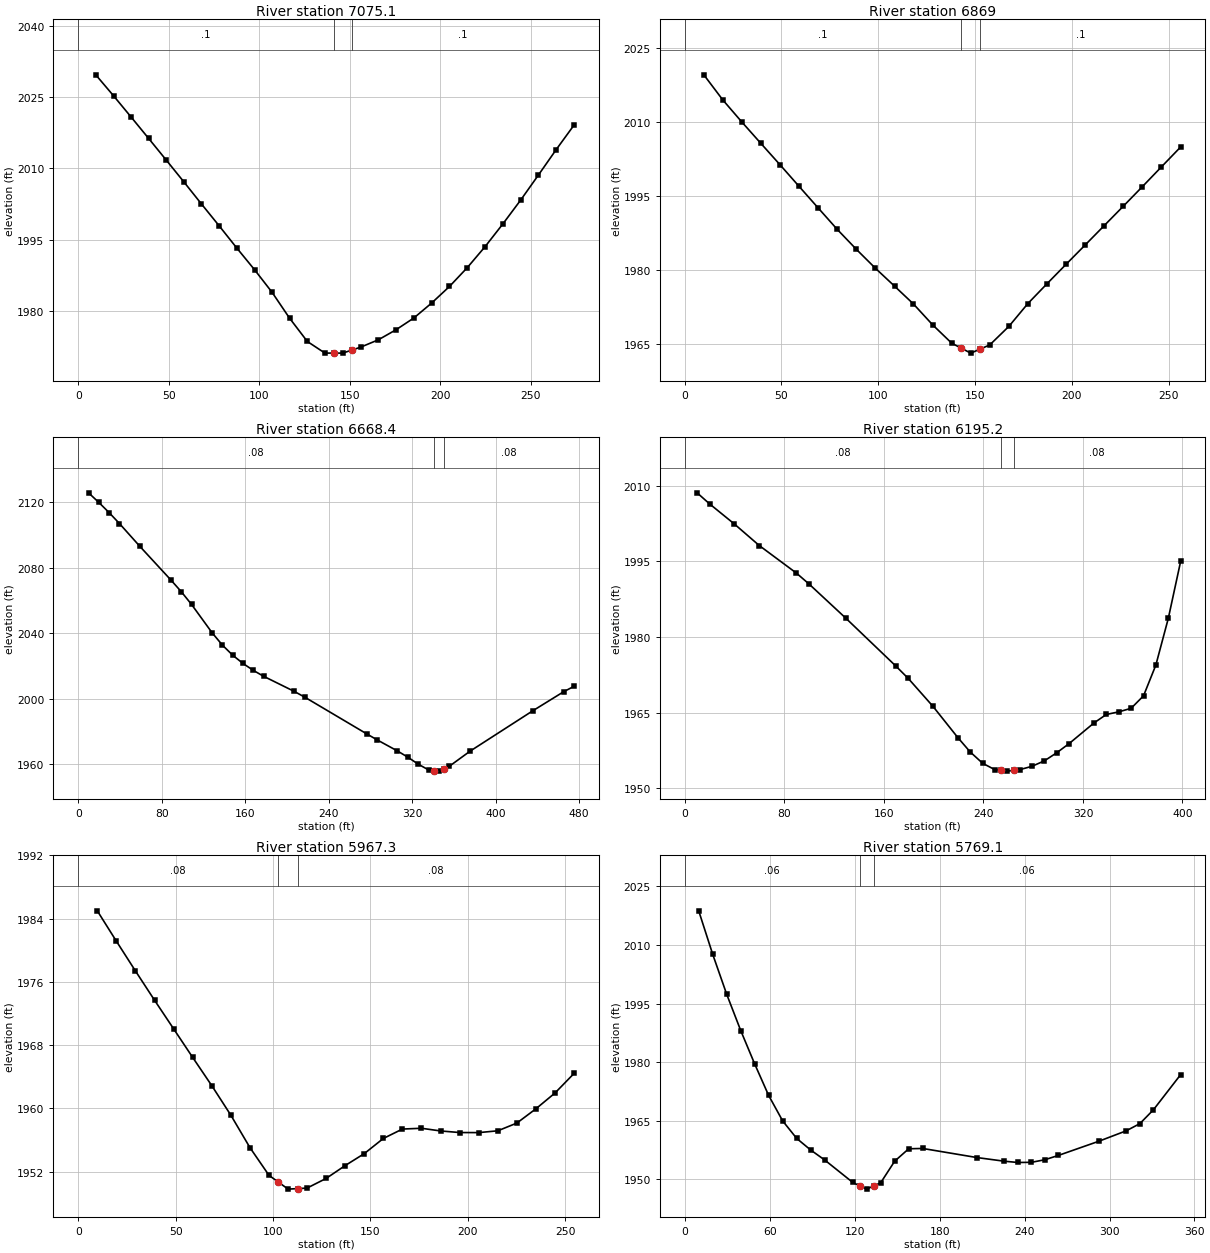
Type RM Length L Ch R = 1 ,7075.1  ,211,206.1,203.6
XS GIS Cut Line= 3
      1844933.36      158245.529     1844814.279      158311.835
      1844702.71      158392.465
#Sta/Elev= 30
     9.7 2029.69    19.5 2025.29    29.2 2020.82    38.9 2016.31    48.7 2011.72
    58.4 2007.15    68.1 2002.51    77.9  1997.9    87.6 1993.25    97.4 1988.69
   107.1 1983.93   116.8 1978.47   126.6 1973.58   136.3 1971.14   141.1 1971.14
   146.1 1971.13   151.1 1971.76     156 1972.38   165.8 1973.93   175.6 1976.05
   185.5 1978.54   195.3 1981.68   205.1 1985.15     215 1989.14   224.8 1993.54
   234.6 1998.31   244.5 2003.36   254.3 2008.63   264.1 2013.97     274 2019.15
#Mann= 3 , 0 , 0
       0      .1       0   141.1    .045       0   151.1      .1       0
Bank Sta=141.1,151.1
XS Rating Curve= 0 ,0
Exp/Cntr=0.3,0.1

Type RM Length L Ch R = 1 ,6869    ,196.8,200.6,204.3
XS GIS Cut Line= 2
     1844776.132      158067.568     1844588.651      158242.119
#Sta/Elev= 28
     9.9 2019.53    19.7 2014.44    29.6 2009.94    39.4 2005.62    49.3 2001.28
    59.1 1996.92      69 1992.53    78.8 1988.21    88.7 1984.16    98.5 1980.34
   108.4 1976.71   118.2 1973.08   128.1 1968.86   137.9 1965.16   142.8 1964.15
   147.8 1963.13   152.8 1963.98   157.6 1964.79   167.5 1968.56   177.3 1973.18
   187.2  1977.2     197 1981.12   206.9 1985.05   216.7 1988.96   226.6 1992.91
   236.5 1996.89   246.3 2000.88   256.2  2004.9
#Mann= 3 , 0 , 0
       0      .1       0   142.8    .045       0   152.8      .1       0
Bank Sta=142.8,152.8
XS Rating Curve= 0 ,0
Exp/Cntr=0.3,0.1

Type RM Length L Ch R = 1 ,6668.4  ,481.1,473.2,465.3
XS GIS Cut Line= 3
     1844894.115      157951.201     1844590.267      157986.757
     1844447.805      158078.328
#Sta/Elev= 30
     9.9 2125.91    19.7 2120.06    29.6 2113.81    39.5 2107.12    59.2 2093.06
    88.8 2072.57    98.7 2065.45   108.6 2057.61   128.3 2040.27   138.2 2032.68
     148 2026.55   157.9 2021.48   167.8 2017.24   177.6 2013.64   207.2 2004.31
   217.1 2000.84   276.3 1978.44   286.2 1974.79   305.9 1967.92   315.9 1964.09
   325.8 1959.84   335.8 1956.29   340.8 1955.92   345.8 1955.56   350.8 1957.07
   355.7 1958.55   375.7 1967.84   435.4 1992.39   465.3 2004.18   475.3 2007.51
#Mann= 3 , 0 , 0
       0     .08       0   340.8    .045       0   350.8     .08       0
Bank Sta=340.8,350.8
XS Rating Curve= 0 ,0
Exp/Cntr=0.3,0.1

Type RM Length L Ch R = 1 ,6195.2  ,231.7,228,224.2
XS GIS Cut Line= 3
     1844451.273      157467.953       1844294.5      157606.948
     1844186.556      157762.094
#Sta/Elev= 30
      10 2008.61      20 2006.42    39.9 2002.43    59.9 1998.16    89.8 1992.68
    99.8 1990.55   129.7 1983.69   169.6 1974.26   179.6  1971.8   199.5 1966.25
   219.5 1960.05   229.4 1957.21   239.4 1954.96   249.3 1953.68   254.3 1953.54
   259.3  1953.4   264.3 1953.55   269.2 1953.69   279.1 1954.36   289.1 1955.45
     299 1957.05     309 1958.88   328.9 1962.96   338.8 1964.64   348.8 1965.16
   358.7 1965.86   368.7 1968.34   378.6 1974.44   388.6  1983.7   398.5    1995
#Mann= 3 , 0 , 0
       0     .08       0   254.3    .045       0   264.3     .08       0
Bank Sta=254.3,264.3
XS Rating Curve= 0 ,0
Exp/Cntr=0.3,0.1

Type RM Length L Ch R = 1 ,5967.3  ,200.6,198.2,195.8
XS GIS Cut Line= 2
     1844110.252      157445.326     1844006.814      157678.061
#Sta/Elev= 28
     9.8 1984.99    19.6 1981.15    29.4 1977.38    39.2 1973.68      49 1970.06
    58.8 1966.44    68.6 1962.87    78.4 1959.13    88.2 1955.03      98 1951.52
   102.8 1950.67   107.8 1949.78   112.8 1949.85   117.5 1949.91   127.3 1951.13
   137.1 1952.76   146.9 1954.27   156.7 1956.19   166.5 1957.38   176.3 1957.48
   186.1 1957.14   195.9 1956.94   205.7 1956.93   215.5 1957.16   225.3 1958.14
   235.1 1959.95   244.9 1961.95   254.7 1964.43
#Mann= 3 , 0 , 0
       0     .08       0   102.8    .045       0   112.8     .08       0
Bank Sta=102.8,112.8
XS Rating Curve= 0 ,0
Exp/Cntr=0.3,0.1

Type RM Length L Ch R = 1 ,5769.1  ,359.6,361.7,363.7
XS GIS Cut Line= 3
     1843913.504      157369.048     1843863.778      157529.619
     1843885.599      157710.385
#Sta/Elev= 29
     9.9 2018.73    19.8 2007.59    29.7 1997.34    39.6 1988.06    49.4 1979.56
    59.3 1971.47    69.2 1964.95    79.1 1960.47      89  1957.5    98.9 1954.94
   118.7  1949.2   123.5 1948.36   128.5 1947.49   133.5 1948.31   138.4 1949.11
   148.3 1954.65   158.2 1957.82   168.1  1957.9   206.4 1955.57   225.6 1954.64
   235.2 1954.31   244.8 1954.35   254.3 1955.01   263.9 1956.12   292.7 1959.78
   311.8 1962.42   321.4 1964.25     331  1967.8   350.2 1976.79
#Mann= 3 , 0 , 0
       0     .06       0   123.5    .045       0   133.5     .06       0
Bank Sta=123.5,133.5
XS Rating Curve= 0 ,0
Exp/Cntr=0.3,0.1

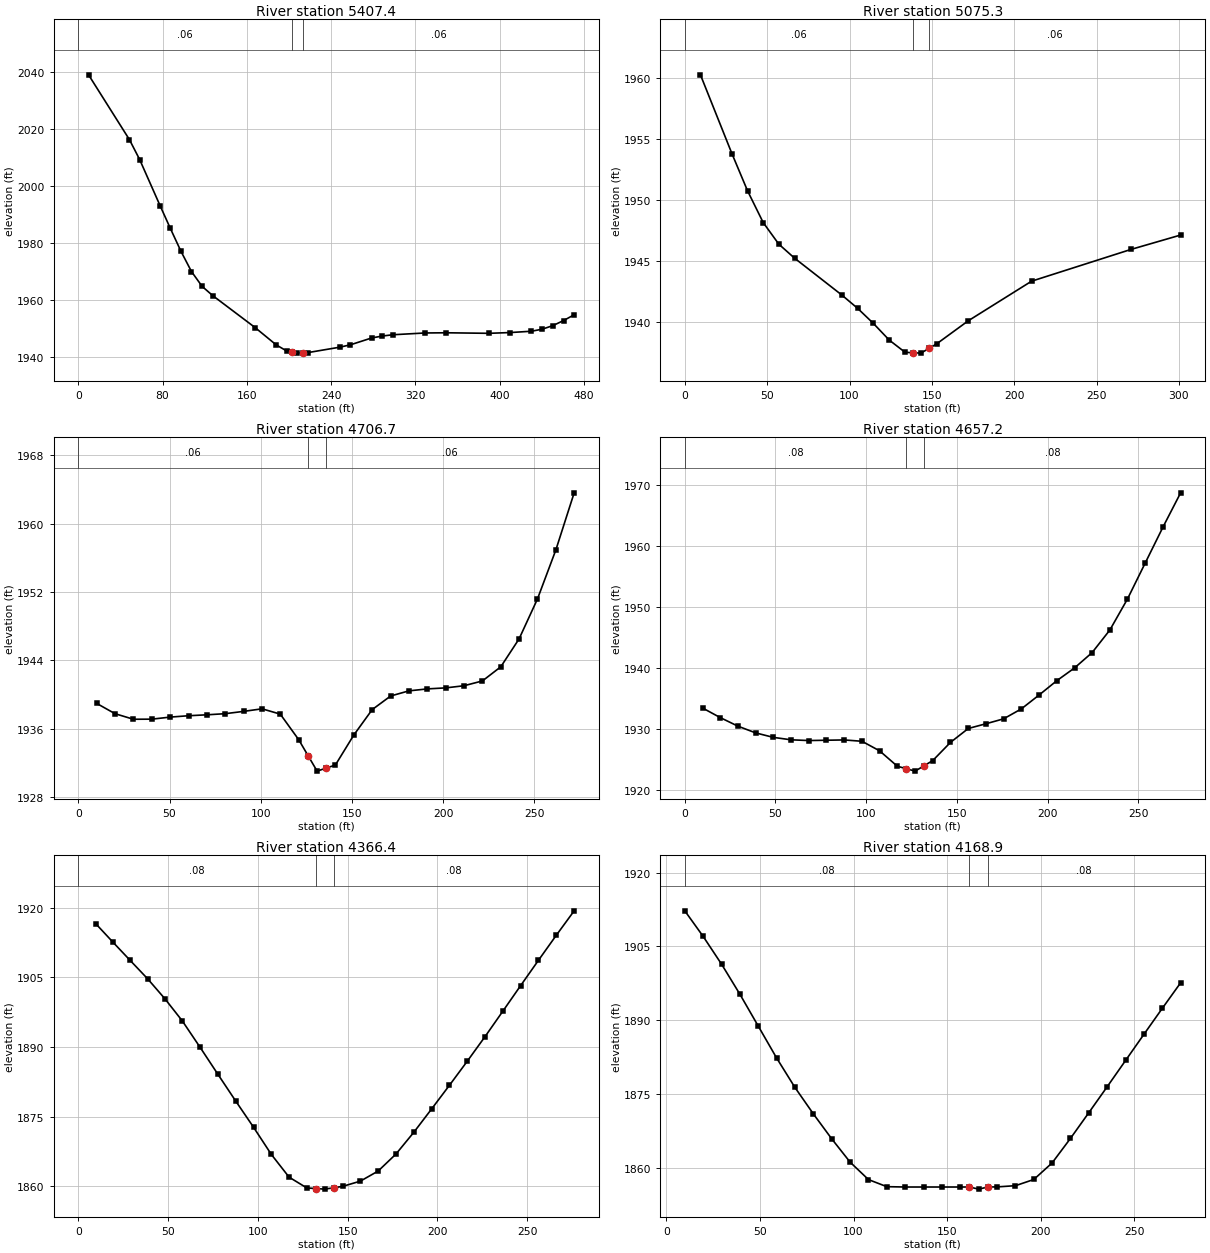
Type RM Length L Ch R = 1 ,5407.4  ,333.4,332.1,330.9
XS GIS Cut Line= 4
     1843605.189      157210.039     1843576.784      157292.622
     1843498.677      157478.009     1843611.351      157621.029
#Sta/Elev= 30
     9.7 2038.88    48.5 2016.17    58.2 2009.21    77.6 1993.03    87.3  1985.1
    97.4 1977.06   107.4 1969.95   117.5 1964.76   127.6 1961.52   167.8 1950.33
   187.9 1944.24     198 1942.09     203 1941.73     208 1941.38     213 1941.48
   218.1 1941.58   248.3 1943.47   258.3  1944.3   278.4 1946.69   288.5 1947.37
   298.6 1947.82     329 1948.44   349.2 1948.51   389.7 1948.32   409.9 1948.59
   430.1 1949.05   440.2 1949.76   450.3 1951.01   460.5 1952.78   470.6 1954.82
#Mann= 3 , 0 , 0
       0     .06       0     203    .045       0     213     .06       0
Bank Sta=203,213
XS Rating Curve= 0 ,0
Exp/Cntr=0.3,0.1

Type RM Length L Ch R = 1 ,5075.3  ,373.4,368.6,363.8
XS GIS Cut Line= 4
     1843262.519      157162.335     1843234.888      157243.432
     1843193.716      157361.239     1843263.236      157419.191
#Sta/Elev= 19
     9.5 1960.27    28.6 1953.82    38.1 1950.77    47.6 1948.17    57.1  1946.4
    66.6 1945.26    95.3 1942.24   104.9 1941.15   114.5 1939.91   124.1 1938.55
   133.7 1937.55   138.3 1937.51   143.3 1937.48   148.3 1937.87   152.9 1938.24
   172.1 1940.13   210.5 1943.37   270.8 1945.97     301 1947.15
#Mann= 3 , 0 , 0
       0     .06       0   138.3    .045       0   148.3     .06       0
Bank Sta=138.3,148.3
XS Rating Curve= 0 ,0
Exp/Cntr=0.3,0.1

Type RM Length L Ch R = 1 ,4706.7  ,50.7,49.4,48.2
XS GIS Cut Line= 2
      1842882.73      157039.357     1842856.394      157309.908
#Sta/Elev= 29
    10.1 1938.97    20.1 1937.77    30.2 1937.12    40.3 1937.13    50.3 1937.37
    60.4 1937.53    70.5 1937.64    80.5 1937.77    90.6 1938.04   100.7 1938.34
   110.7 1937.72   120.8 1934.73   125.9 1932.87   130.9 1931.05   135.9 1931.41
   140.9 1931.76     151 1935.27   161.1 1938.25   171.2 1939.84   181.2 1940.44
   191.3 1940.67   201.4 1940.79   211.4 1941.04   221.5  1941.6   231.6 1943.26
   241.6 1946.52   251.7  1951.2   261.8 1956.95   271.8 1963.61
#Mann= 3 , 0 , 0
       0     .06       0   125.9    .045       0   135.9     .06       0
Bank Sta=125.9,135.9
XS Rating Curve= 0 ,0
Exp/Cntr=0.3,0.1

Type RM Length L Ch R = 1 ,4657.2  ,290.1,290.9,291.6
XS GIS Cut Line= 2
     1842826.979      157039.657      1842814.05      157312.797
#Sta/Elev= 30
     9.8 1933.46    19.5  1931.9    29.3 1930.49    39.1 1929.39    48.8 1928.66
    58.6 1928.26    68.4 1928.14    78.1 1928.19    87.9 1928.24    97.7 1928.02
   107.4 1926.46   117.2 1923.94     122 1923.55     127 1923.14     132 1924.03
   136.7 1924.86   146.5 1927.84   156.3 1930.11     166 1930.88   175.8 1931.69
   185.6 1933.32   195.3 1935.57   205.1 1937.92   214.9 1940.01   224.6 1942.52
   234.4 1946.22   244.1 1951.29   253.9 1957.18   263.7 1963.06   273.4 1968.64
#Mann= 3 , 0 , 0
       0     .08       0     122    .045       0     132     .08       0
Bank Sta=122,132
XS Rating Curve= 0 ,0
Exp/Cntr=0.3,0.1

Type RM Length L Ch R = 1 ,4366.4  ,199.7,197.5,195.3
XS GIS Cut Line= 3
     1842522.584      157007.074     1842539.682      157062.375
      1842523.65      157280.072
#Sta/Elev= 30
     9.6 1916.57    19.3 1912.54    28.9 1908.61    38.6 1904.66    48.2 1900.37
    57.9  1895.6    67.8 1889.92    77.7 1884.12    87.6 1878.37    97.6 1872.69
   107.5 1866.84   117.4 1861.94   127.3 1859.61   132.3 1859.49   137.3 1859.36
   142.3 1859.66   147.2 1859.95   157.1 1861.08     167 1863.25   176.9  1866.9
   186.9 1871.61   196.8 1876.63   206.7 1881.71   216.6 1886.88   226.6 1892.23
   236.5  1897.7   246.4  1903.2   256.3 1908.64   266.2 1914.01   276.2  1919.3
#Mann= 3 , 0 , 0
       0     .08       0   132.3    .045       0   142.3     .08       0
Bank Sta=132.3,142.3
XS Rating Curve= 0 ,0
Exp/Cntr=0.3,0.1

Type RM Length L Ch R = 1 ,4168.9  ,131.9,132.8,133.8
XS GIS Cut Line= 2
     1842330.802      156991.171       1842340.5      157265.927
#Sta/Elev= 30
     9.8 1912.24    19.6 1907.05    29.5 1901.37    39.3 1895.26    49.1 1888.79
    58.9 1882.32    68.7 1876.33    78.6 1870.93    88.4 1865.87    98.2 1861.15
     108 1857.61   117.8 1856.17   127.6  1856.1   137.5  1856.1   147.3  1856.1
   157.1  1856.1   161.9  1856.1  166.97 1855.67   171.9 1856.11   176.7 1856.12
   186.6 1856.37   196.4 1857.63   206.2    1861     216 1865.98   225.8  1871.2
   235.7 1876.52   245.5 1881.84   255.3 1887.15   265.1 1892.42   274.9 1897.61
#Mann= 3 , 0 , 0
     9.8     .08       0   161.9    .045       0   171.9     .08       0
Bank Sta=161.9,171.9
XS Rating Curve= 0 ,0
Exp/Cntr=0.3,0.1

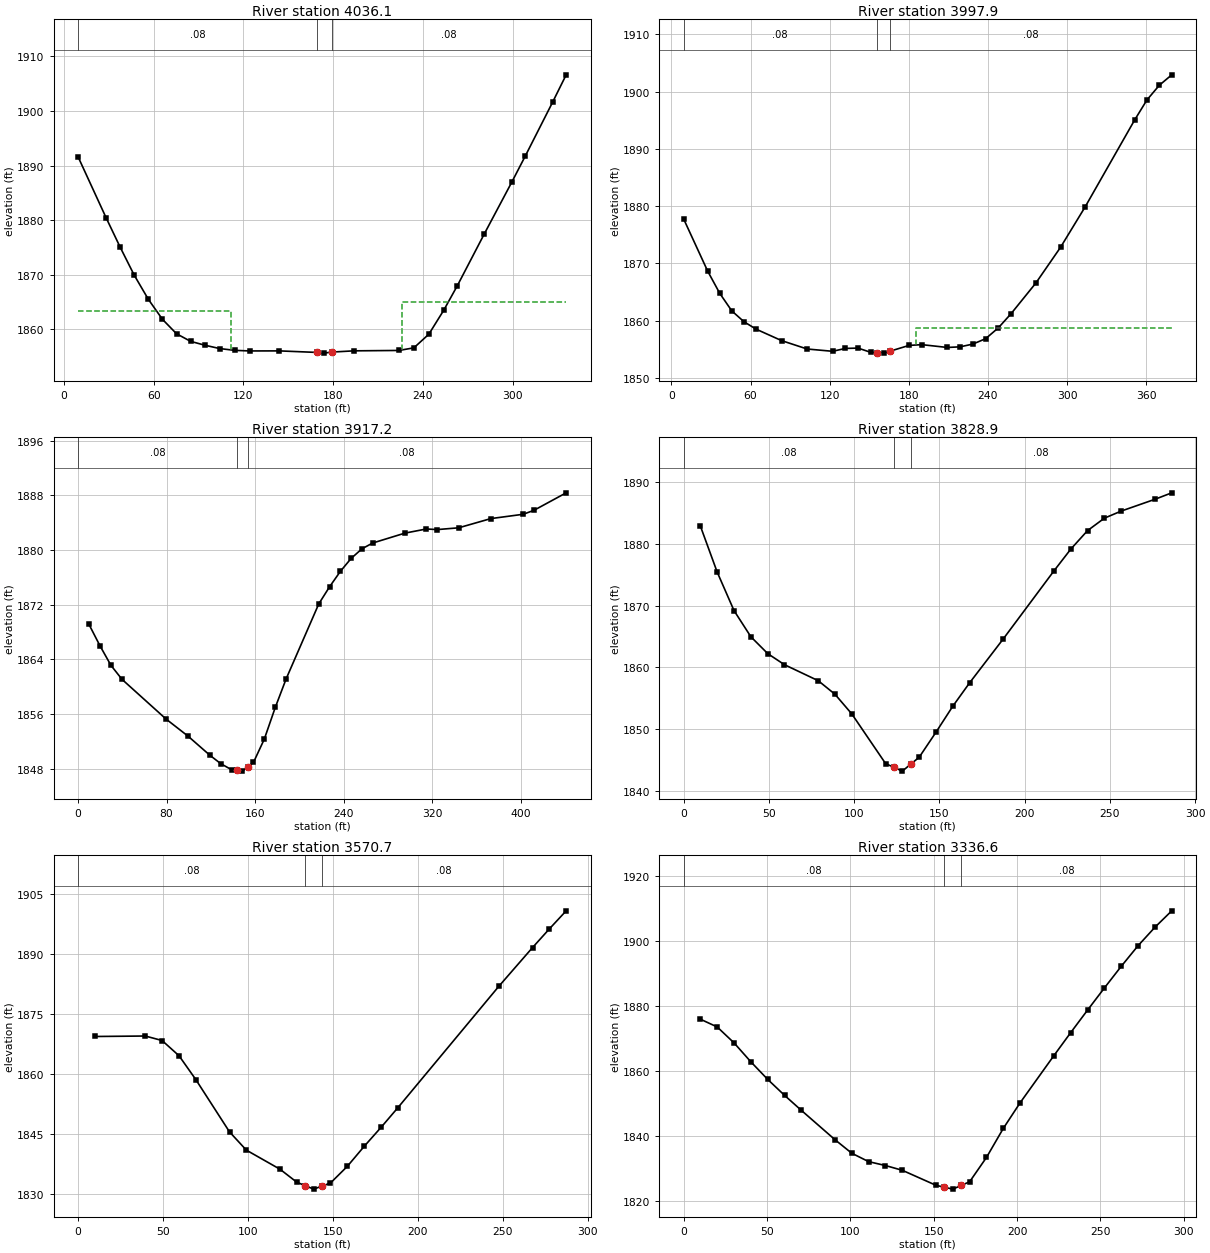
Type RM Length L Ch R = 1 ,4036.1  ,33.3,38.2,43.1
XS GIS Cut Line= 4
     1842266.517      156997.371     1842205.285      157068.808
     1842203.017      157228.691      1842226.83      157306.932
#Sta/Elev= 27
     9.4 1891.66    28.2 1880.46    37.6 1875.07      47 1869.94    56.5 1865.49
    65.9 1861.84    75.3  1859.2    84.7 1857.81    94.1 1857.11   104.1 1856.49
   114.1 1856.16   124.1 1856.05   144.1 1856.06     169 1855.78     174 1855.65
     179 1855.84     194 1856.07     224 1856.14     234 1856.62     244 1859.12
     254 1863.53   263.1 1868.03   281.2 1877.56   299.4 1886.95   308.5 1891.77
   326.7  1901.6   335.8 1906.63
#Mann= 3 , 0 , 0
     9.4     .08       0     169    .045       0     179     .08       0
#XS Ineff= 2 , 0
          111.58 1863.28  226.09         1865.06
Permanent Ineff=
       F       F
Bank Sta=169,179
XS Rating Curve= 0 ,0
Exp/Cntr=0.3,0.1

Type RM Length L Ch R = 1 ,3997.9  ,61.1,80.7,100.2
XS GIS Cut Line= 4
     1842225.696      156995.103     1842191.678      157049.532
     1842142.919      157236.629     1842123.643      157356.825
#Sta/Elev= 30
     9.2  1877.8    27.5 1868.64    36.7 1864.74    45.8 1861.69      55  1859.8
    64.2  1858.5    83.5  1856.5   102.9 1855.03   122.2 1854.63   131.9 1855.13
   141.5 1855.19   151.2 1854.44   155.9 1854.38   160.9 1854.31   165.9 1854.66
   180.2 1855.66   189.9 1855.79   209.2  1855.3   218.9 1855.41   228.5 1855.89
   238.2 1856.83   247.9 1858.74   257.5  1861.2   276.3 1866.56     295  1872.8
   313.7 1879.88   351.2 1895.06   360.5 1898.55   369.9 1901.12   379.3 1902.94
#Mann= 3 , 0 , 0
     9.2     .08       0   155.9    .045       0   165.9     .08       0
#XS Ineff= 2 , 0
                          185.23         1858.63
Permanent Ineff=
       F       F
Bank Sta=155.9,165.9
XS Rating Curve= 0 ,0
Exp/Cntr=0.3,0.1

Type RM Length L Ch R = 1 ,3917.2  ,89.5,88.3,87.1
XS GIS Cut Line= 4
     1842204.151      156983.764     1842161.062      157073.344
     1842051.072      157116.433     1841928.365        157303.1
#Sta/Elev= 30
     9.9 1869.14    19.9 1865.99    29.8 1863.13    39.8 1861.08    79.5 1855.28
    99.4 1852.77   119.1 1849.98   128.9 1848.75   138.8 1847.85   143.6 1847.76
   148.6 1847.65   153.6 1848.29   158.5 1848.92   168.3 1852.34   178.2 1856.97
     188 1861.15   217.5 1872.13   227.2 1874.62     237 1876.89   246.7 1878.78
   256.4 1880.18   266.1 1881.03   295.2 1882.48   314.7 1883.09   324.4    1883
   343.8 1883.26   372.9 1884.61   402.1 1885.24   411.8 1885.82   440.9 1888.38
#Mann= 3 , 0 , 0
       0     .08       0   143.6    .045       0   153.6     .08       0
Bank Sta=143.6,153.6
XS Rating Curve= 0 ,0
Exp/Cntr=0.3,0.1

Type RM Length L Ch R = 1 ,3828.9  ,271.2,258.2,254.5
XS GIS Cut Line= 2
     1842216.051      156950.765     1841957.457      157073.597
#Sta/Elev= 25
     9.9 1882.87    19.7 1875.46    29.6 1869.21    39.5 1864.97    49.4 1862.24
    59.2 1860.45      79 1857.86    88.8 1855.67    98.7 1852.48   118.5 1844.45
   123.3 1843.85   128.3 1843.23   133.3 1844.37   138.2 1845.48   148.1 1849.55
   157.9 1853.73   167.8 1857.53   187.6 1864.66   217.2 1875.62   227.1 1879.15
   236.9 1882.14   246.8 1884.16   256.7 1885.31   276.4 1887.21   286.3 1888.26
#Mann= 3 , 0 , 0
       0     .08       0   123.3    .045       0   133.3     .08       0
Bank Sta=123.3,133.3
XS Rating Curve= 0 ,0
Exp/Cntr=0.3,0.1

Type RM Length L Ch R = 1 ,3570.7  ,222.8,234.1,245.4
XS GIS Cut Line= 2
     1842052.927      156731.615     1841815.344      156893.236
#Sta/Elev= 21
     9.9 1869.37    39.6 1869.49    49.5 1868.37    59.5 1864.56    69.4 1858.61
    89.2 1845.59    99.1 1841.05   118.9 1836.29   128.8 1833.05   133.7  1832.2
   138.7 1831.33   143.7 1832.09   148.6 1832.85   158.5    1837   168.4 1841.97
   178.4 1846.74   188.3 1851.64   247.7 1881.89   267.5 1891.53   277.4 1896.18
   287.3 1900.69
#Mann= 3 , 0 , 0
       0     .08       0   133.7    .045       0   143.7     .08       0
Bank Sta=133.7,143.7
XS Rating Curve= 0 ,0
Exp/Cntr=0.3,0.1

Type RM Length L Ch R = 1 ,3336.6  ,257.7,258.8,260.1
XS GIS Cut Line= 2
     1842005.944      156593.582     1841713.409      156604.896
#Sta/Elev= 28
    10.1 1875.98    20.2 1873.59    30.3  1868.7    40.4 1862.87    50.5 1857.47
    60.6 1852.57    70.7 1847.95    90.9 1838.92   100.9 1834.79     111 1832.21
   121.1 1831.01   131.2 1829.55   151.4 1824.94   156.5 1824.34   161.5 1823.76
   166.5 1824.88   171.6 1826.03   181.7 1833.51   191.8 1842.44   201.9 1850.32
   222.1 1864.77   232.2 1871.85   242.3 1878.77   252.4 1885.57   262.5 1892.22
   272.6 1898.56   282.7 1904.22   292.8 1909.28
#Mann= 3 , 0 , 0
       0     .08       0   156.5    .045       0   166.5     .08       0
Bank Sta=156.5,166.5
XS Rating Curve= 0 ,0
Exp/Cntr=0.3,0.1

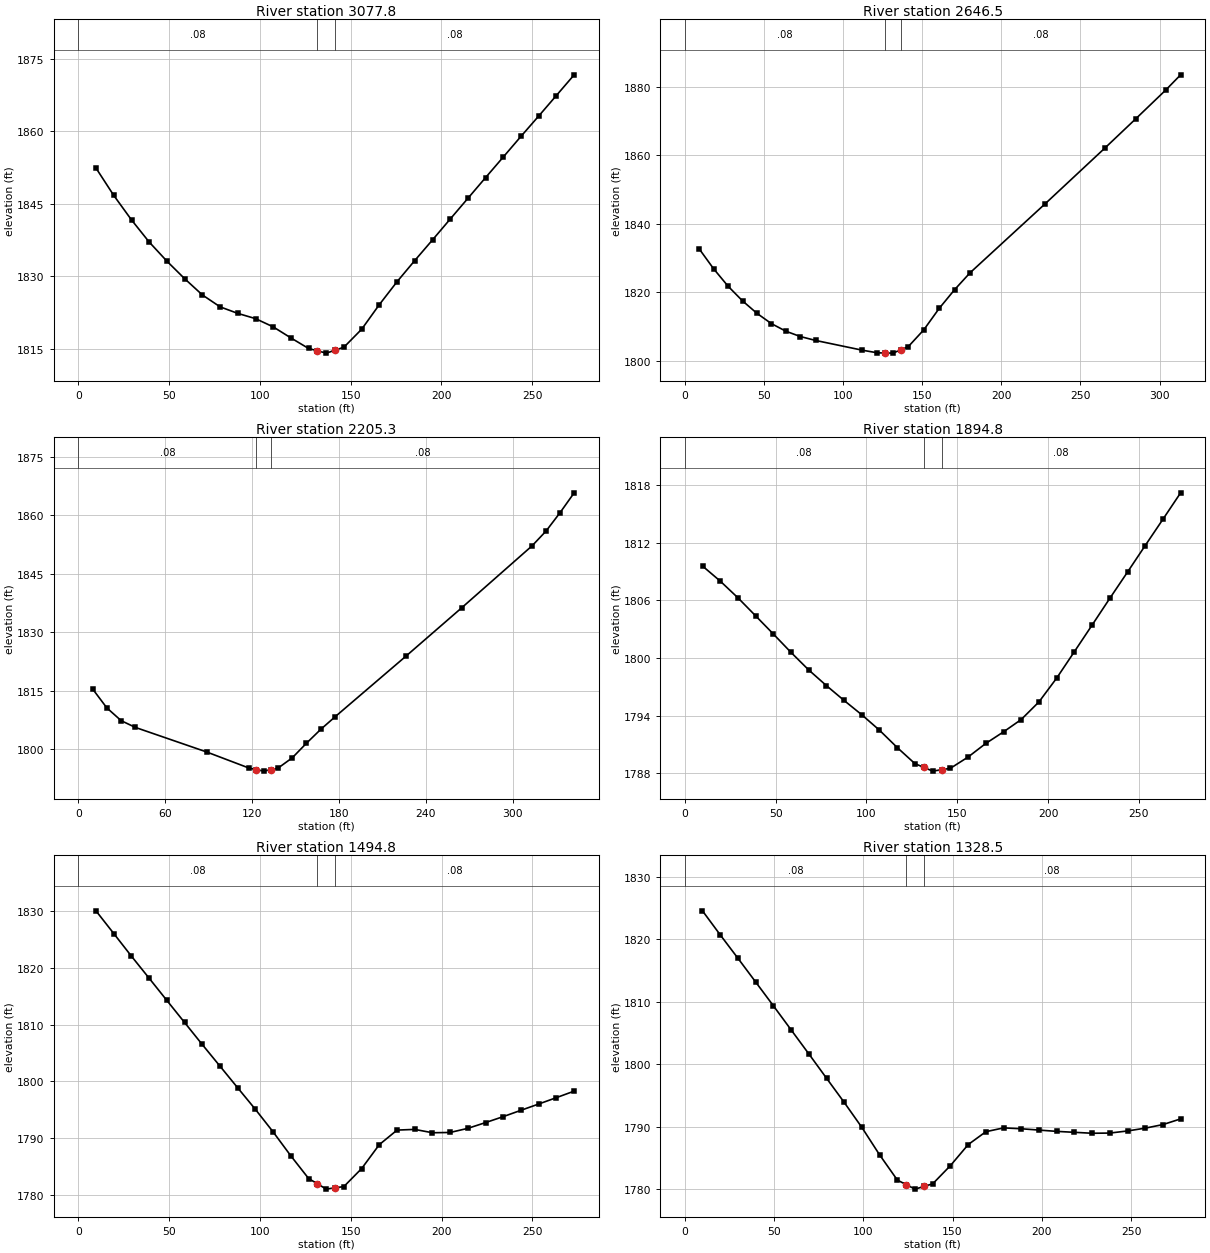
Type RM Length L Ch R = 1 ,3077.8  ,436.1,431.3,426.3
XS GIS Cut Line= 3
     1841978.756      156343.613     1841842.184      156341.196
     1841705.746        156337.7
#Sta/Elev= 30
     9.8 1852.37    19.5 1846.75    29.3 1841.66      39 1837.09    48.8 1833.11
    58.5  1829.5    68.3 1826.12    78.1 1823.64    87.8 1822.29    97.6  1821.2
   107.3  1819.5   117.1  1817.2   126.8 1815.02   131.6 1814.54   136.6 1814.05
   141.6 1814.68   146.3 1815.28   156.1 1819.02   165.8 1824.11   175.6 1828.88
   185.3 1833.24   195.1 1837.53   204.8 1841.83   214.6 1846.15   224.3 1850.43
   234.1 1854.72   243.8 1858.98   253.6 1863.21   263.3 1867.45   273.1 1871.74
#Mann= 3 , 0 , 0
       0     .08       0   131.6    .045       0   141.6     .08       0
Bank Sta=131.6,141.6
XS Rating Curve= 0 ,0
Exp/Cntr=0.3,0.1

Type RM Length L Ch R = 1 ,2646.5  ,442.1,441.2,440.2
XS GIS Cut Line= 4
     1841852.404      155932.552     1841779.523       155936.57
     1841674.609      155958.697     1841578.117      156050.335
#Sta/Elev= 24
     9.1 1832.67    18.2 1826.86    27.4 1821.73    36.5 1817.46    45.6 1813.83
    54.7 1810.83    63.9  1808.6      73 1807.05    82.7  1805.9     112 1803.07
   121.7 1802.29   126.5 1802.24   131.5  1802.2   136.5 1803.17   141.2 1804.09
     151    1809   160.7 1815.25   170.5 1820.76   180.2 1825.66   227.7 1845.85
   265.8 1862.29   284.8 1870.62   303.8 1879.05   313.3 1883.54
#Mann= 3 , 0 , 0
       0     .08       0   126.5    .045       0   136.5     .08       0
Bank Sta=126.5,136.5
XS Rating Curve= 0 ,0
Exp/Cntr=0.3,0.1

Type RM Length L Ch R = 1 ,2205.3  ,310.5,310.6,310.7
XS GIS Cut Line= 3
     1841763.512      155515.569     1841561.622      155560.657
     1841434.216      155607.532
#Sta/Elev= 20
     9.9 1815.42    19.7 1810.58    29.6  1807.3    39.4 1805.57    88.7 1799.26
   118.2  1795.1   123.1 1794.73   128.1 1794.35   133.1 1794.74   137.9  1795.1
   147.8 1797.76   157.6  1801.5   167.5 1805.07   177.3 1808.26   226.3 1823.83
     265  1836.3   313.5 1852.16   323.2 1855.97   332.9  1860.7   342.6 1865.77
#Mann= 3 , 0 , 0
       0     .08       0   123.1    .045       0   133.1     .08       0
Bank Sta=123.1,133.1
XS Rating Curve= 0 ,0
Exp/Cntr=0.3,0.1

Type RM Length L Ch R = 1 ,1894.8  ,411,400,389
XS GIS Cut Line= 3
     1841704.711       155212.24     1841571.381      155241.486
     1841438.051      155270.733
#Sta/Elev= 30
     9.8 1809.56    19.5    1808    29.3 1806.25      39 1804.38    48.8 1802.48
    58.5 1800.57    68.2 1798.75      78 1797.11    87.7 1795.57    97.5 1794.07
   107.2 1792.47     117 1790.66   126.7 1788.99   131.5 1788.61   136.5 1788.21
   141.5 1788.36   146.2  1788.5     156 1789.68   165.7 1791.09   175.5  1792.3
   185.2 1793.58     195 1795.42   204.8 1797.91   214.5 1800.65   224.3 1803.43
     234  1806.2   243.8 1808.95   253.5  1811.7   263.3 1814.45     273 1817.19
#Mann= 3 , 0 , 0
       0     .08       0   131.5    .045       0   141.5     .08       0
Bank Sta=131.5,141.5
XS Rating Curve= 0 ,0
Exp/Cntr=0.3,0.1

Type RM Length L Ch R = 1 ,1494.8  ,166.6,166.2,165.8
XS GIS Cut Line= 3
     1841506.762      154813.524     1841405.675       154905.25
     1841304.589      154996.977
#Sta/Elev= 30
     9.7 1830.08    19.5 1826.08    29.2  1822.1      39 1818.19    48.7  1814.3
    58.5 1810.39    68.2 1806.52      78 1802.69    87.7 1798.89    97.5 1795.07
   107.2 1791.12     117 1786.88   126.8 1782.88   131.5 1781.98   136.5 1781.01
   141.5 1781.25   146.2 1781.46     156 1784.64   165.7 1788.85   175.5 1791.42
   185.2 1791.54     195 1790.95   204.7    1791   214.5 1791.73   224.2 1792.74
     234  1793.8   243.7 1794.91   253.5 1796.02   263.2 1797.14     273 1798.29
#Mann= 3 , 0 , 0
       0     .08       0   131.5    .045       0   141.5     .08       0
Bank Sta=131.5,141.5
XS Rating Curve= 0 ,0
Exp/Cntr=0.3,0.1

Type RM Length L Ch R = 1 ,1328.5  ,143.2,146,148.8
XS GIS Cut Line= 2
     1841396.632      154686.452     1841194.605      154877.165
#Sta/Elev= 30
     9.9 1824.58    19.8 1820.75    29.8 1816.97    39.7 1813.18    49.6 1809.38
    59.5 1805.54    69.5 1801.66    79.4 1797.77    89.3  1793.9    99.2 1789.89
   109.1 1785.51   119.1 1781.45     124 1780.73     129    1780     134 1780.43
   138.9 1780.85   148.8 1783.76   158.8 1787.14   168.7  1789.2   178.6 1789.81
   188.5 1789.67   198.4 1789.46   208.4 1789.25   218.3  1789.1   228.2 1788.95
   238.1 1788.98   248.1 1789.32     258 1789.77   267.9 1790.34   277.8 1791.25
#Mann= 3 , 0 , 0
       0     .08       0     124    .045       0     134     .08       0
Bank Sta=124,134
XS Rating Curve= 0 ,0
Exp/Cntr=0.3,0.1

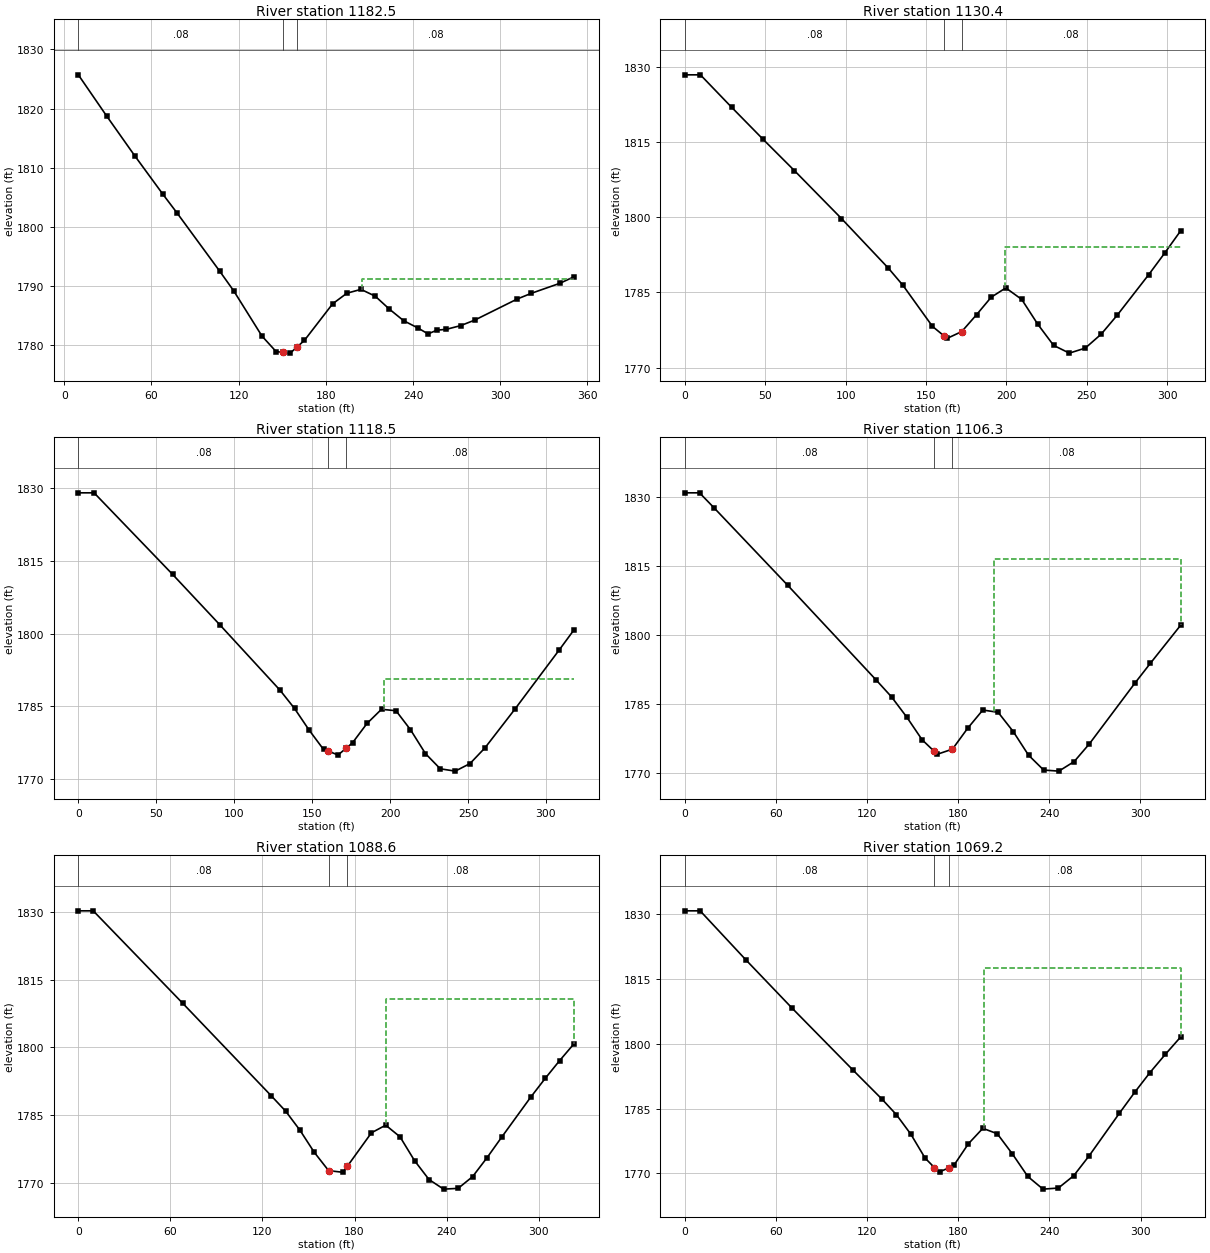
Type RM Length L Ch R = 1 ,1182.5  ,51.8,52.1,52.3
XS GIS Cut Line= 3
     1841315.821      154591.095     1841165.249      154698.053
     1841165.513      154864.235
#Sta/Elev= 29
     9.7 1825.72    29.2 1818.76    48.6 1812.02      68 1805.51    77.8 1802.33
   106.9 1792.58   116.6 1789.24   136.1 1781.58   145.8 1778.97   150.5 1778.85
   155.5 1778.71   160.5 1779.81   165.3 1780.87   184.7 1787.04   194.5 1788.83
   204.2 1789.48     214 1788.33   223.8 1786.13   233.6 1784.18   243.3 1782.97
  250.34 1781.96  256.51 1782.59   262.9 1782.73   272.7 1783.35   282.4 1784.28
   311.8 1787.86   321.5 1788.82   341.1 1790.51   350.9 1791.62
#Mann= 3 , 0 , 0
     9.7     .08       0   150.5    .045       0   160.5     .08       0
#XS Ineff= 2 , 0
                          205.03         1791.18
Permanent Ineff=
       F       F
Bank Sta=150.5,160.5
XS Rating Curve= 0 ,0
Exp/Cntr=0.3,0.1

Type RM Length L Ch R = 1 ,1130.4  ,11.5,12,12.5
XS GIS Cut Line= 4
     1841301.047      154563.462     1841187.977      154620.429
     1841126.695      154660.133     1841042.108      154728.321
#Sta/Elev= 25
       0  1828.4     9.7  1828.4    29.2  1821.9    48.7 1815.53    68.2 1809.28
    97.4 1799.74   126.6 1789.83   135.7 1786.39     154 1778.22  161.17 1776.33
   163.1 1775.83   172.2 1777.19   181.4 1780.55   190.5 1784.04   199.6  1785.9
   209.5  1783.6   219.4 1778.69   229.3 1774.44   239.1 1772.89     249 1773.89
   258.9 1776.67   268.8 1780.43   288.5 1788.56   298.4 1792.85   308.3 1797.28
#Mann= 3 , 0 , 0
       0     .08       0  161.17    .045       0   172.2     .08       0
#XS Ineff= 2 , 0
                           199.4         1794.14
Permanent Ineff=
       F       F
Bank Sta=161.17,172.2
XS Rating Curve= 0 ,0
Exp/Cntr=0.3,0.1

Type RM Length L Ch R = 1 ,1118.5  ,12.4,12.2,12
XS GIS Cut Line= 4
     1841292.416      154550.515     1841194.882      154603.166
     1841107.706      154656.681     1841025.708      154722.279
#Sta/Elev= 24
       0 1828.99    10.1 1828.99    60.5 1812.18    90.7 1801.83   129.4 1788.33
   138.7 1784.57     148 1780.14   157.3 1776.13  160.37 1775.79   166.6 1774.98
  171.95 1776.41   175.9 1777.49   185.2 1781.48   194.5  1784.4   203.8  1784.1
   213.1 1780.19   222.7 1775.27   232.2 1772.14   241.8 1771.66   251.3 1773.22
   260.9 1776.46     280 1784.39   308.6 1796.66   318.1 1800.81
#Mann= 3 , 0 , 0
       0     .08       0  160.37    .045       0  171.95     .08       0
#XS Ineff= 2 , 0
                           195.9         1790.65
Permanent Ineff=
       F       F
Bank Sta=160.37,171.95
XS Rating Curve= 0 ,0
Exp/Cntr=0.3,0.1

Type RM Length L Ch R = 1 ,1106.3  ,18.5,17.7,16.8
XS GIS Cut Line= 4
     1841285.511      154533.253     1841186.251      154593.672
     1841084.401      154657.544     1841014.487       154714.51
#Sta/Elev= 23
       0 1830.81     9.7 1830.81    19.4 1827.51    67.8 1810.74   126.2 1790.14
   136.2 1786.52   146.3  1782.1   156.3 1777.23   164.3 1774.71   166.3 1774.08
   176.3 1775.19   186.3 1779.71   196.3 1783.68   206.4 1783.18   216.4 1778.98
   226.4 1773.89   236.4 1770.65   246.4 1770.42   256.5  1772.5   266.5 1776.34
   296.5 1789.52   306.6 1793.79   326.6 1802.07
#Mann= 3 , 0 , 0
       0     .08       0   164.3    .045       0   176.3     .08       0
#XS Ineff= 2 , 0
                          203.79         1816.49
Permanent Ineff=
       F       F
Bank Sta=164.3,176.3
XS Rating Curve= 0 ,0
Exp/Cntr=0.3,0.1

Type RM Length L Ch R = 1 ,1088.6  ,19.7,19.5,19.3
XS GIS Cut Line= 4
      1841274.29      154518.579     1841174.167      154578.135
     1841097.348      154630.787     1841002.403      154692.932
#Sta/Elev= 24
       0 1830.21     9.7 1830.21      68 1809.75   125.8 1789.23   135.1 1785.86
   144.4 1781.65   153.7 1776.77   163.1 1772.69   172.4 1772.33  175.29 1773.66
     191 1781.07   200.3 1782.76   209.6 1780.19   219.1  1774.9   228.5 1770.73
     238  1768.6   247.5 1768.77   256.9 1771.36   266.4 1775.59   275.8 1780.07
   294.7 1788.92   304.2  1793.1   313.6 1797.04   323.1 1800.82
#Mann= 3 , 0 , 0
       0     .08       0   163.1    .045       0  175.29     .08       0
#XS Ineff= 2 , 0
                          200.19         1810.77
Permanent Ineff=
       F       F
Bank Sta=163.1,175.29
XS Rating Curve= 0 ,0
Exp/Cntr=0.3,0.1

Type RM Length L Ch R = 1 ,1069.2  ,19.7,19.1,18.5
XS GIS Cut Line= 4
     1841261.343      154496.138     1841168.988       154557.42
     1841091.306      154611.798     1840992.909      154681.711
#Sta/Elev= 27
       0  1830.8    10.1  1830.8    40.3 1819.41    70.5 1808.31   110.8 1793.89
   129.8 1787.19   139.3 1783.59   148.8 1779.07   158.2 1773.53  164.36 1771.33
   167.7 1770.34  173.63 1771.25   177.2 1771.89   186.7 1776.86   196.2 1780.43
   205.7 1779.18   215.7 1774.48   225.8 1769.28   235.8 1766.35   245.9  1766.6
     256 1769.45     266 1773.98   286.1 1783.93   296.2 1788.79   306.2 1793.34
   316.3 1797.55   326.4 1801.58
#Mann= 3 , 0 , 0
       0     .08       0  164.36    .045       0  173.63     .08       0
#XS Ineff= 2 , 0
                          197.04         1817.56
Permanent Ineff=
       F       F
Bank Sta=164.36,173.63
XS Rating Curve= 0 ,0
Exp/Cntr=0.3,0.1