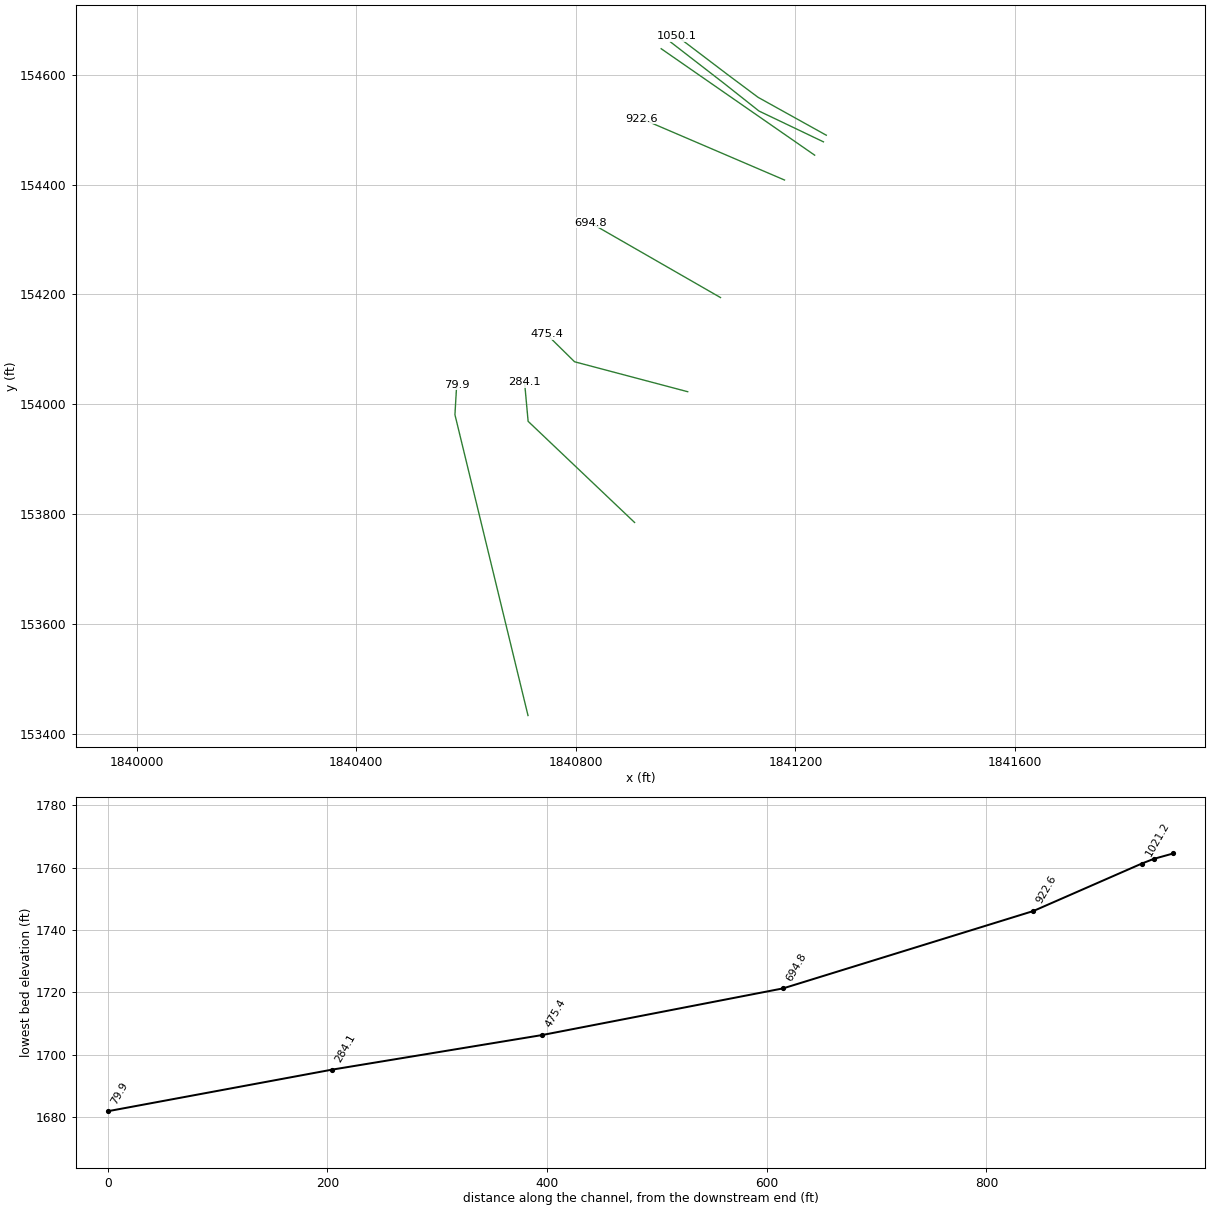
HEC-RAS study Burk Creek.prj: Burk Creek

--- Burk Creek.g01 (geometry) --- (continued)

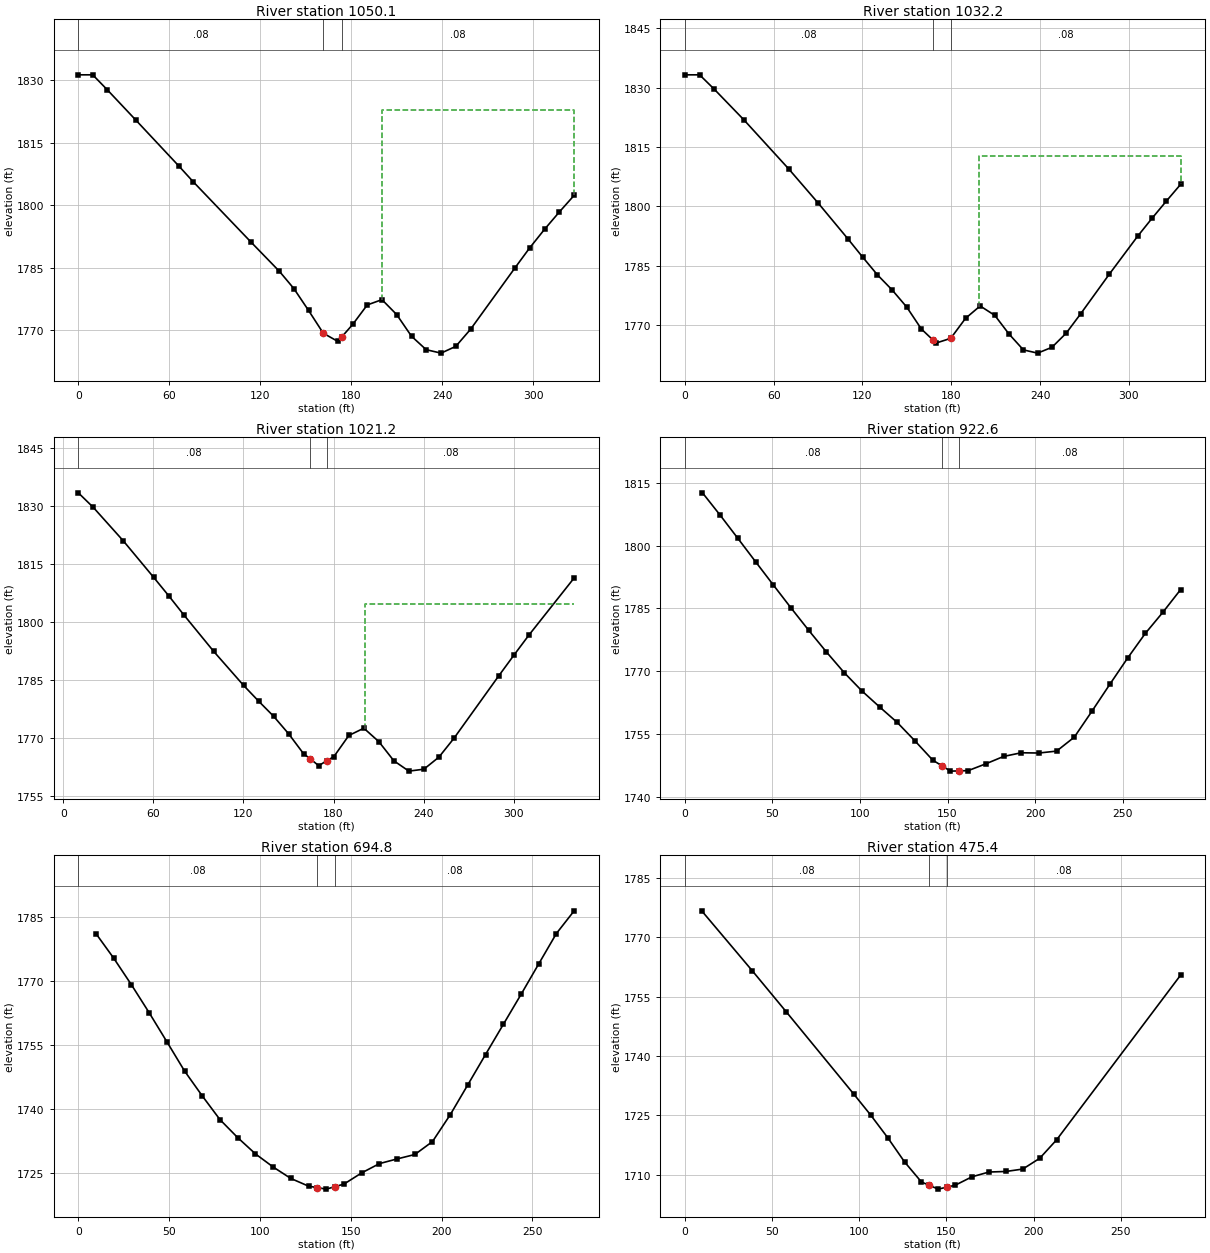
Type RM Length L Ch R = 1 ,1050.1  ,18.5,17.8,17.3
XS GIS Cut Line= 4
     1841256.164      154490.096     1841131.873      154559.147
     1841077.496      154599.714     1840984.278      154670.491
#Sta/Elev= 27
       0 1831.28     9.5 1831.28      19 1827.73    37.9 1820.44    66.4 1809.38
    75.8 1805.64   113.7 1791.26   132.7 1784.15   142.2 1780.03   151.9 1774.78
   161.6 1769.33   171.3 1767.35  173.69 1768.41     181 1771.44   190.6 1776.11
   200.3 1777.38     210 1773.81   219.8 1768.61   229.5 1765.38   239.3 1764.56
     249 1766.18   258.8  1770.3   288.1 1785.02   297.8 1789.81   307.6 1794.26
   317.3 1798.39   327.1 1802.39
#Mann= 3 , 0 , 0
       0     .08       0   161.6    .045       0  173.69     .08       0
#XS Ineff= 2 , 0
                          200.19         1822.88
Permanent Ineff=
       F       F
Bank Sta=161.6,173.69
XS Rating Curve= 0 ,0
Exp/Cntr=0.3,0.1

Type RM Length L Ch R = 1 ,1032.2  ,9.6,11,12.3
XS GIS Cut Line= 4
     1841250.986      154478.012       1841133.6      154534.116
     1841071.454      154583.314     1840972.194      154660.133
#Sta/Elev= 29
       0 1833.27      10 1833.27      20 1829.59      40 1821.84    70.1 1809.49
    90.1  1800.8   110.1 1791.78   120.1 1787.14   130.1 1782.64     140 1778.83
   149.9 1774.48   159.8 1768.92  167.32 1766.25   169.7 1765.37   179.6 1766.56
   189.6 1771.62   199.5 1774.76   209.4 1772.37     219 1767.65   228.7 1763.64
   238.3 1762.82     248  1764.3   257.6 1767.87   267.3 1772.73   286.6 1782.74
   305.9 1792.43   315.6 1796.96   325.2 1801.28   334.9 1805.54
#Mann= 3 , 0 , 0
       0     .08       0  167.32    .045       0   179.6     .08       0
#XS Ineff= 2 , 0
                          198.84         1812.84
Permanent Ineff=
       F       F
Bank Sta=167.32,179.6
XS Rating Curve= 0 ,0
Exp/Cntr=0.3,0.1

Type RM Length L Ch R = 1 ,1021.2  ,94.6,98.7,102.8
XS GIS Cut Line= 2
      1841235.01      154453.717     1840955.406      154647.663
#Sta/Elev= 28
      10 1833.28      20  1829.5      40 1820.84    60.1 1811.46    70.1 1806.71
    80.1  1801.8   100.1 1792.31   120.1 1783.47   130.1 1779.41   140.1 1775.49
   150.1 1770.96   160.1 1765.78  164.31 1764.56   170.1 1762.72  175.55    1764
   180.2 1765.04   190.2 1770.53   200.2 1772.41   210.2 1768.93   220.2 1763.98
   230.2 1761.31   240.2 1761.81   250.2 1764.93   260.2 1769.79   290.2 1786.02
   300.3 1791.37   310.3 1796.56   340.3 1811.27
#Mann= 3 , 0 , 0
      10     .08       0  164.31    .045       0  175.55     .08       0
#XS Ineff= 2 , 0
                          200.64         1804.58
Permanent Ineff=
       F       F
Bank Sta=164.31,175.55
XS Rating Curve= 0 ,0
Exp/Cntr=0.3,0.1

Type RM Length L Ch R = 1 ,922.6   ,230.2,227.8,225.4
XS GIS Cut Line= 2
     1841180.059      154408.463     1840919.849      154519.982
#Sta/Elev= 30
    10.1 1812.66    20.2 1807.31    30.3 1801.77    40.4 1796.19    50.6 1790.59
    60.7  1785.1    70.8 1779.75    80.9 1774.58      91 1769.66   101.1 1765.29
   111.2 1761.46   121.3 1757.74   131.4 1753.34   141.6 1748.72   146.7  1747.4
   151.7  1746.1   156.7 1746.16   161.8 1746.22   171.9 1747.85     182 1749.61
   192.1 1750.49   202.2 1750.43   212.3 1750.89   222.4 1754.23   232.5 1760.45
   242.7 1766.88   252.8 1773.12   262.9 1779.02     273 1784.11   283.1 1789.52
#Mann= 3 , 0 , 0
       0     .08       0   146.7    .045       0   156.7     .08       0
Bank Sta=146.7,156.7
XS Rating Curve= 0 ,0
Exp/Cntr=0.3,0.1

Type RM Length L Ch R = 1 ,694.8   ,214.1,219.4,224.6
XS GIS Cut Line= 3
     1841063.477      154194.306     1840945.117        154262.3
     1840826.757      154330.293
#Sta/Elev= 30
     9.8 1781.09    19.5 1775.38    29.2 1769.19      39 1762.62    48.8 1755.79
    58.5 1748.96    68.2 1743.16      78 1737.58    87.7 1733.39    97.5 1729.57
   107.3 1726.48     117 1723.81   126.8    1722   131.5 1721.67   136.5 1721.31
   141.5 1721.91   146.3  1722.5     156 1725.11   165.8 1727.29   175.5 1728.38
   185.3 1729.42     195 1732.45   204.8 1738.75   214.5 1745.78   224.2 1752.83
     234 1759.89   243.8 1766.94   253.5 1774.06   263.2 1781.16     273 1786.48
#Mann= 3 , 0 , 0
       0     .08       0   131.5    .045       0   141.5     .08       0
Bank Sta=131.5,141.5
XS Rating Curve= 0 ,0
Exp/Cntr=0.3,0.1

Type RM Length L Ch R = 1 ,475.4   ,201.3,191.3,181.3
XS GIS Cut Line= 3
      1841003.69      154022.795     1840797.623      154077.342
     1840746.914      154127.242
#Sta/Elev= 19
     9.7 1776.67    38.8 1761.47    58.1 1751.19    96.9 1730.36   106.6 1725.06
   116.3 1719.38     126 1713.23   135.7 1708.15   140.3 1707.29   145.3 1706.35
   150.3 1706.86     155 1707.33   164.7 1709.47   174.4 1710.67   184.1 1710.81
   193.8 1711.42   203.5 1714.14   213.2 1718.81   284.3 1760.43
#Mann= 3 , 0 , 0
       0     .08       0   140.3    .045       0   150.3     .08       0
Bank Sta=140.3,150.3
XS Rating Curve= 0 ,0
Exp/Cntr=0.3,0.1

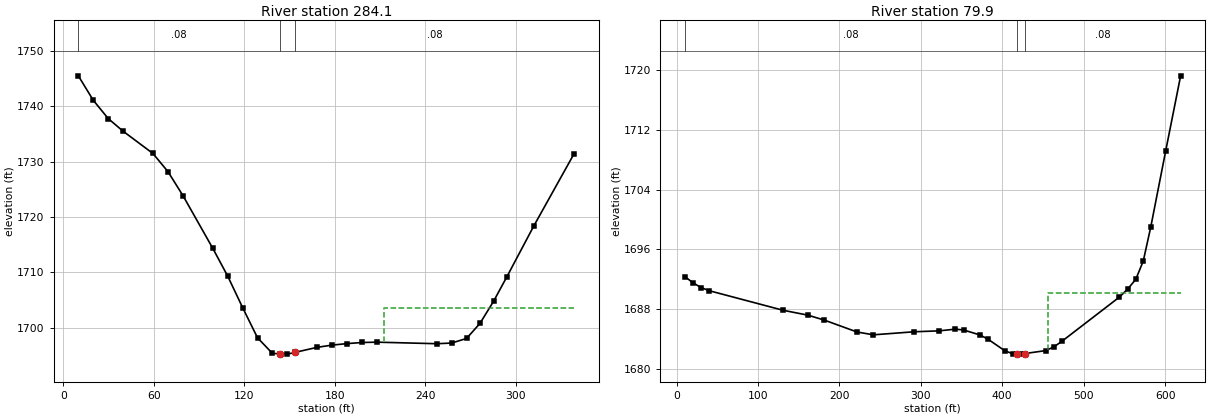
Type RM Length L Ch R = 1 ,284.1   ,215.9,204.2,192.6
XS GIS Cut Line= 3
     1840906.919      153784.605     1840712.974      153968.854
     1840706.509      154039.967
#Sta/Elev= 28
     9.9 1745.51    19.8  1741.1    29.7  1737.8    39.6 1735.51    59.4 1731.49
    69.4  1728.2    79.3 1723.89    99.1 1714.37     109 1709.35   118.9 1703.67
   128.8 1698.21   138.7 1695.39   143.6 1695.33   148.6 1695.26   153.6 1695.57
   168.4 1696.49   178.3 1696.89   188.2 1697.16   198.2 1697.36   208.1 1697.42
   247.7 1697.14   257.6 1697.26   267.5 1698.09   276.4 1700.81   285.4 1704.79
   294.3 1709.25   312.1 1718.39   338.9 1731.47
#Mann= 3 , 0 , 0
     9.9     .08       0   143.6    .045       0   153.6     .08       0
#XS Ineff= 2 , 0
                          212.58         1703.51
Permanent Ineff=
       F       F
Bank Sta=143.6,153.6
XS Rating Curve= 0 ,0
Exp/Cntr=0.3,0.1

Type RM Length L Ch R = 1 ,79.9    ,79.5,79.9,80.2
XS GIS Cut Line= 3
     1840712.772      153432.877     1840579.636      153980.975
     1840582.869      154035.926
#Sta/Elev= 30
    10.1 1692.34    20.1  1691.5    30.2 1690.85    40.3 1690.43   130.9 1687.81
   161.2 1687.16   181.3  1686.5   221.6  1684.9   241.7 1684.52   292.1 1684.93
   322.3 1685.05   342.5 1685.28   352.5 1685.17   372.7  1684.5   382.7 1683.92
   402.9  1682.4     413 1681.97     418 1681.95     423 1681.93     428 1682.01
   453.2  1682.4   463.3 1682.89   473.4 1683.66   543.9 1689.58     554 1690.65
     564 1691.96   573.2 1694.41   582.4 1698.97   600.7 1709.16   619.1 1719.26
#Mann= 3 , 0 , 0
    10.1     .08       0     418    .045       0     428     .08       0
#XS Ineff= 2 , 0
                           455.7         1690.18
Permanent Ineff=
       F       F
Bank Sta=418,428
XS Rating Curve= 0 ,0
Exp/Cntr=0.3,0.1

Chan Stop Cuts=-1
Use User Specified Reach Order=0